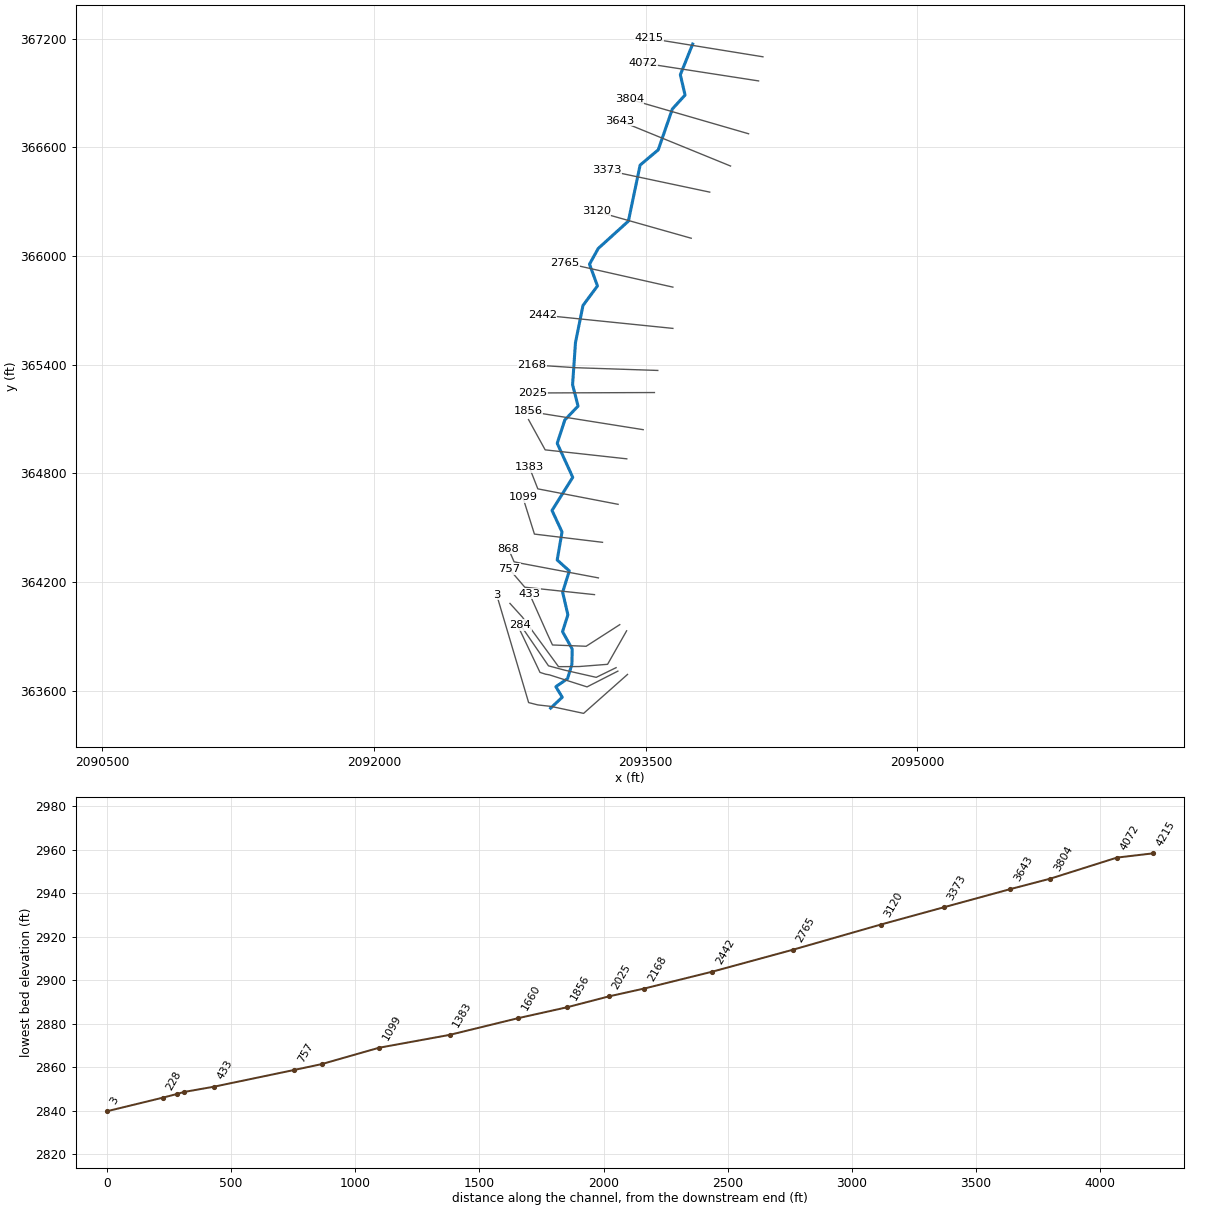
--- KUHNBR.prj (project) ---

Proj Title=KUHNBR
Current Plan=p01
Default Exp/Contr=0.3,0.1
English Units
Geom File=g03
Flow File=f01
Plan File=p01
Y Axis Title=Elevation
X Axis Title(PF)=Main Channel Distance
X Axis Title(XS)=Station
BEGIN DESCRIPTION:
Stream Name- Kuhn Branch
Flood Zone: Zone A
Greenbrier County, WV
County-Wide Study
WVDHSEM-2018-3, Flood Risk Project
HEC-RAS Version: 5.0.7
General Notes:
For the Hydrology regression was used.
END DESCRIPTION:
DSS Export Rating Curves= 0
DSS Export Rating Curve Sorted= 0
DSS Export Volume Flow Curves= 0
DXF OffsetX= 0
DXF OffsetY= 0
DXF ScaleX= 1
DXF ScaleY= 10

--- KUHNBR.p01 (plan) ---

Plan Title=Floodplain
Program Version=5.07
Short Identifier=Floodplain
Geom File=g03
Flow File=f01
Subcritical Flow
K Sum by GR= 0
Std Step Tol= 0.01
Critical Tol= 0.01
Num of Std Step Trials= 20
Max Error Tol= 0.3
Flow Tol Ratio= 0.001
Split Flow NTrial= 30
Split Flow Tol= 0.02
Split Flow Ratio= 0.02
Log Output Level= 0
Friction Slope Method= 1
Unsteady Friction Slope Method= 2
Unsteady Bridges Friction Slope Method= 1
Parabolic Critical Depth
Global Vel Dist= 0 , 0 , 0
Global Log Level= 0
CheckData=True
Encroach Param=-1 ,0,0, 0
Computation Interval=1MIN
Output Interval=1HOUR
Instantaneous Interval=1HOUR
Mapping Interval=1HOUR
Computation Time Step Use Courant=        0
Computation Time Step Use Time Series=    0
Computation Time Step Count To Double=0
Computation Time Step Max Doubling=0
Computation Time Step Max Halving=0
Computation Time Step Residence Courant=0
Run HTab= 0
Run UNet= 0
Run Sediment= 0
Run PostProcess= 0
Run WQNet= 0
Run RASMapper=-1
UNET Theta= 1
UNET Theta Warmup= 1
UNET ZTol= 0.02
UNET ZSATol= 0.02
UNET MxIter= 20
UNET Max Iter WO Improvement= 0
UNET MaxInSteps= 0
UNET DtIC= 0
UNET DtMin= 0
UNET MaxCRTS= 20
UNET WFStab= 2
UNET SFStab= 1
UNET WFX= 1
UNET SFX= 1
UNET 1D Methodology=Finite Difference
UNET DSS MLevel= 4
UNET Pardiso=0
UNET DZMax Abort= 100
UNET Use Existing IB Tables=-1
UNET Froude Reduction=False
UNET Froude Limit= 0.8
UNET Froude Power= 4
UNET D1 Cores= 0
UNET D2 Coriolis=0
UNET D2 Cores= 0
UNET D2 Theta= 1
UNET D2 Theta Warmup= 1
UNET D2 Z Tol= 0.01
UNET D2 Volume Tol= 0.01
UNET D2 Max Iterations= 20
UNET D2 Equation= 0
UNET D2 RampUpFraction=0.1
UNET D2 TimeSlices= 1
UNET D2 BCVolumeCheck=0
UNET D1D2 MaxIter= 0
UNET D1D2 ZTol=0.01
UNET D1D2 QTol=0.1
UNET D1D2 MinQTol=1
Write IC File= 0
Write IC File at Fixed DateTime=0
Write IC File at Sim End=0
Echo Input=False
Echo Parameters=False
Echo Output=False
Write Detailed= 0
HDF Write Warmup=0
HDF Write Time Slices=0
HDF Flush=0
HDF Face Node Velocities=0
HDF Compression= 1
HDF Chunk Size= 1
HDF Spatial Parts= 1
HDF Use Max Rows=0
HDF Fixed Rows= 1
Calibration Method= 0
Calibration Iterations= 20
Calibration Max Change=0.05
Calibration Tolerance=0.2
Calibration Maximum=1.5
Calibration Minimum=0.5
Calibration Optimization Method= 1
WQ AD Non Conservative
WQ ULTIMATE=-1
WQ Max Comp Step=1HOUR
WQ Output Interval=15MIN
WQ Output Selected Increments= 0
WQ Output face flow=0
WQ Output face velocity=0
WQ Output face area=0
WQ Output face dispersion=0
WQ Output cell volume=0
WQ Output cell surface area=0
WQ Output cell continuity=0
WQ Output cumulative cell continuity=0
WQ Output face conc=0
WQ Output face dconc_dx=0
WQ Output face courant=0
WQ Output face peclet=0
WQ Output face adv mass=0
WQ Output face disp mass=0
WQ Output cell mass=0
WQ Output cell source sink temp=0
WQ Output nsm pathways=0
WQ Output nsm derived pathways=0
WQ Output MaxMinRange=-1
WQ Daily Max Min Mean=-1
WQ Daily Range=0
WQ Daily Time=0
WQ Create Restart=0
WQ Fixed Restart=0
WQ System Summary=0
WQ Write To DSS=0
WQ Use Fixed Temperature=0
Sorting and Armoring Iterations= 10
XS Update Threshold= 0.02
Bed Roughness Predictor= 0
Hydraulics Update Threshold= 0.02
Energy Slope Method= 1
Volume Change Method= 1
Sediment Retention Method= 0
XS Weighting Method= 0
Number of US Weighted Cross Sections= 1
Number of DS Weighted Cross Sections= 1
Upstream XS Weight=0
Main XS Weight=1
Downstream XS Weight=0
Number of DS XS's Weighted with US Boundary= 1
Upstream Boundary Weight= 1
Weight of XSs Associated with US Boundary= 0
Number of US XS's Weighted with DS Boundary= 1
Downstream Boundary Weight= 0.5
Weight of XSs Associated with DS Boundary= 0.5
Percentile Method= 0
Sediment Output Level= 3
Mass or Volume Output= 0
Output Increment Type= 1
Profile and TS Output Increment= 1
XS Output Flag= 0
XS Output Increment= 10
Write Gradation File= 0
Read Gradation Hotstart= 0
Write HDF5 File= 1
Write Binary Output= 1
Write DSS Sediment File= 0
SV Curve= 0
Specific Gage Flag= 0

--- KUHNBR.f01 (steady flow) ---

Flow Title=H3b_combinedFlows
Program Version=5.07
Number of Profiles= 6
Profile Names=f1p,f10p,f4p,f2p,f02p,f1pplus
River Rch & RM=KUHNBR,Main            ,4215
     610     323     429     516     850     901
Boundary for River Rch & Prof#=KUHNBR,Main            , 1
Up Type= 0
Dn Type= 3
Dn Slope=0.02625
Boundary for River Rch & Prof#=KUHNBR,Main            , 2
Up Type= 0
Dn Type= 3
Dn Slope=0.02625
Boundary for River Rch & Prof#=KUHNBR,Main            , 3
Up Type= 0
Dn Type= 3
Dn Slope=0.02625
Boundary for River Rch & Prof#=KUHNBR,Main            , 4
Up Type= 0
Dn Type= 3
Dn Slope=0.02625
Boundary for River Rch & Prof#=KUHNBR,Main            , 5
Up Type= 0
Dn Type= 3
Dn Slope=0.02625
Boundary for River Rch & Prof#=KUHNBR,Main            , 6
Up Type= 0
Dn Type= 3
Dn Slope=0.02625
DSS Import GetInterval= 0
DSS Import GetPeak= 0
DSS Import FillOption= 0

--- KUHNBR.g03 (geometry) ---

Geom Title=Geometry
Program Version=5.03

River Reach=KUHNBR          ,Main
Reach XY= 30
2093760.17400004367169.5880000292093692.05500002367000.128000021
2093718.09444825366888.084855393 2093647.9915369366811.133013397
2093570.03100006366585.6490000192093469.98400004      366501.375
2093405.24000002366192.118000016 2093239.0370001366041.308000028
 2093190.6250001 365954.473000022093234.61900003365834.216999993
2093154.62500001365726.5740000012093113.14200003365521.515000001
 2093097.1760001365289.122999996 2093127.4260001365171.029000014
     2093054.288365094.2430000452093012.33100007364965.601999998
2093098.14100008      364777.684     2092983.691364594.884000003
2093038.90700002364476.1459999982093012.21480544364321.269451588
2093079.12904166364261.2846634092093042.36467947364143.605436832
2093071.24323066364018.8277992462093041.70556007363925.716764987
2093094.98334067363830.3501578272093093.51844855363745.555051818
2093069.38398243363666.4443176542093004.83719547363621.919144243
2093040.10877849363563.9202444852092976.07731728363503.276904002

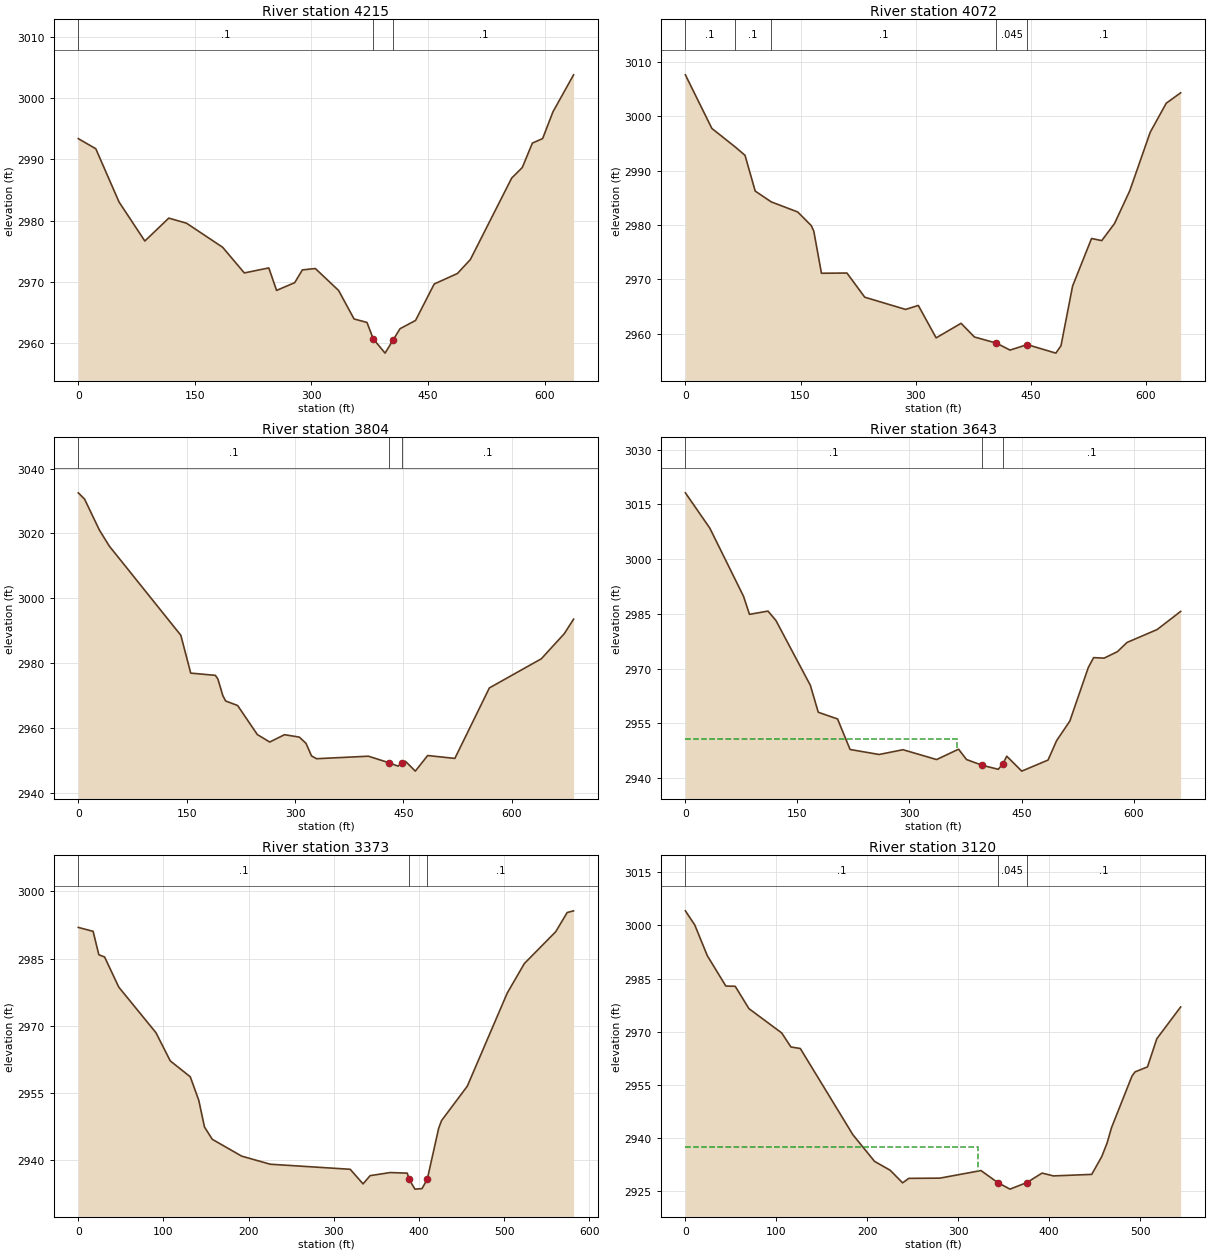
Type RM Length L Ch R = 1 ,4215    ,141.3,143.1,145.3
XS GIS Cut Line= 2
2094148.15418737367099.2438271042093519.14084694367201.187368485
#Sta/Elev= 30
       0 2993.41    22.5 2991.76    52.4 2983.05    85.6 2976.66   116.4 2980.41
   139.3 2979.57   185.7 2975.64   213.6 2971.44   245.1 2972.26   255.1 2968.58
   278.4 2969.85   288.3 2971.94     305 2972.16   334.9 2968.57   354.8 2963.91
   371.4 2963.34   379.5 2960.65   394.7 2958.32   405.3 2960.53   413.9 2962.31
   433.9 2963.67   457.9 2969.63   487.8 2971.35   504.4 2973.63   557.6 2986.96
   571.2 2988.68   584.2 2992.68   597.4 2993.42   610.7  2997.8   637.2 3003.85
#Mann= 3 ,-1 , 0
       0      .1       0   379.5    .045       0   405.3      .1       0
Bank Sta=379.5,405.3
XS Rating Curve= 0 ,0
Exp/Cntr=0.3,0.1

Type RM Length L Ch R = 1 ,4072    ,265.6,268.2,262.4
XS GIS Cut Line= 2
2094124.03044126 366966.110984592093486.34105475367064.801008692
#Sta/Elev= 30
       0 3007.65    34.5 2997.78    64.4 2994.43    77.7 2992.83      91 2986.24
   111.9 2984.25   146.4 2982.39     164 2979.89   167.3 2978.87   177.3 2971.11
   210.5 2971.15   233.7  2966.7   286.9 2964.45   303.5 2965.18   326.7 2959.21
   359.2 2961.89   376.6 2959.37   405.1 2958.25     423 2956.96   445.4 2957.97
   482.7  2956.4   489.4 2957.77   504.5 2968.75   529.2 2977.51   542.5 2977.12
   559.1 2980.26     579  2986.3   605.6 2997.06   626.5 3002.42   645.3 3004.34
#Mann= 5 ,-1 , 0
       0      .1       0    64.4      .1       0   111.9      .1       0
   405.1    .045       0   445.4      .1       0
Bank Sta=405.1,445.4
XS Rating Curve= 0 ,0
Exp/Cntr=0.3,0.1

Type RM Length L Ch R = 1 ,3804    ,161.4,160.9,159.6
XS GIS Cut Line= 2
2094068.72064753366674.378935319 2093410.4256516366865.251948968
#Sta/Elev= 30
       0 3032.51     8.7 3030.57    29.2 3021.03    42.9  3016.1   141.9  2988.6
   155.6 2976.94   189.7 2976.25   193.2 2975.11     200 2970.01   203.9 2968.35
   220.5 2966.95   247.8    2958   264.9  2955.7   285.4 2957.96   305.9 2957.21
   315.1 2955.31   322.8 2951.41   329.8 2950.56   401.5 2951.33   429.3 2949.36
   442.5 2948.27   447.9 2949.31   452.8 2949.75   466.4 2946.73   483.5 2951.54
   521.1 2950.65   568.9 2972.38   640.8 2981.36   672.6 2989.11   685.4 2993.57
#Mann= 3 ,-1 , 0
       0      .1       0   429.3    .045       0   447.9      .1       0
Bank Sta=429.3,447.9
XS Rating Curve= 0 ,0
Exp/Cntr=0.3,0.1

Type RM Length L Ch R = 1 ,3643    ,267.4,269.5,268.6
XS GIS Cut Line= 2
2093969.21073708366496.2586248952093355.38047727366746.779455309
#Sta/Elev= 30
       0 3018.19    32.7 3008.52    77.9  2989.8    85.8 2984.89   110.6 2985.78
   121.2 2983.21   167.3 2965.43   177.9 2958.05   203.7 2956.22   220.5 2947.85
   259.4 2946.48   291.3 2947.79   336.3 2945.09   365.7 2947.93   376.4 2945.09
   397.5 2943.52   418.9 2942.42   425.2 2943.99   430.2 2946.01   450.3 2941.92
   485.5 2944.96   496.9 2950.26   514.6 2955.62   539.4 2970.33   546.5 2973.03
   560.6 2972.89   578.4 2974.67   591.2 2977.18   631.5 2980.72     663 2985.69
#Mann= 3 ,-1 , 0
       0      .1       0   397.5    .045       0   425.2      .1       0
#XS Ineff= 2 , 0
       0  363.25 2950.69               0
Permanent Ineff=
       F       F
Bank Sta=397.5,425.2
XS Rating Curve= 0 ,0
Exp/Cntr=0.3,0.1

Type RM Length L Ch R = 1 ,3373    ,253,253.3,251.8
XS GIS Cut Line= 2
2093854.33414261366352.2094426692093285.30334294366472.710082599
#Sta/Elev= 30
       0 2991.95    17.4 2991.07    24.1 2985.85    30.9 2985.34    47.6  2978.6
    91.2 2968.44     108 2962.15   131.5  2958.6   141.5 2953.33   148.2 2947.38
   157.3 2944.65   191.8 2940.89   225.4 2939.08   319.3 2937.95   334.4 2934.69
   342.7 2936.53   366.2 2937.22   386.3 2937.09   388.5  2935.7   395.3 2933.52
   403.6 2933.63   409.8 2935.73   423.2 2947.12   426.6 2948.83   456.8  2956.5
   503.7 2977.29   523.8 2983.88   560.7    2991   574.1 2995.27   581.6 2995.65
#Mann= 3 ,-1 , 0
       0      .1       0   388.5    .045       0   409.8      .1       0
Bank Sta=388.5,409.8
XS Rating Curve= 0 ,0
Exp/Cntr=0.3,0.1

Type RM Length L Ch R = 1 ,3120    ,350.7,354.4,351.6
XS GIS Cut Line= 2
2093752.18464266 366097.615888982093228.00685897366245.831676094
#Sta/Elev= 30
       0 3004.12    10.4 3000.09    24.1 2991.47    44.5 2982.89    54.8 2982.83
    69.9 2976.52   105.9 2969.67   116.1  2965.7   126.4 2965.27   184.3 2940.91
   208.1 2933.41   225.2 2930.93   238.9 2927.36   245.7 2928.63   279.8 2928.69
   325.1 2930.83   343.7 2927.41     357 2925.59   375.6 2927.45   392.3 2930.12
   404.8 2929.32   446.9 2929.75     458 2934.81   463.9 2938.68   468.6 2942.89
   491.2 2957.51   494.6 2958.68   508.2 2960.08   518.5 2968.03   544.7 2976.99
#Mann= 3 ,-1 , 0
       0      .1       0   343.7    .045       0   375.6      .1       0
#XS Ineff= 2 , 0
       0  322.24 2937.55               0
Permanent Ineff=
       F       F
Bank Sta=343.7,375.6
XS Rating Curve= 0 ,0
Exp/Cntr=0.3,0.1

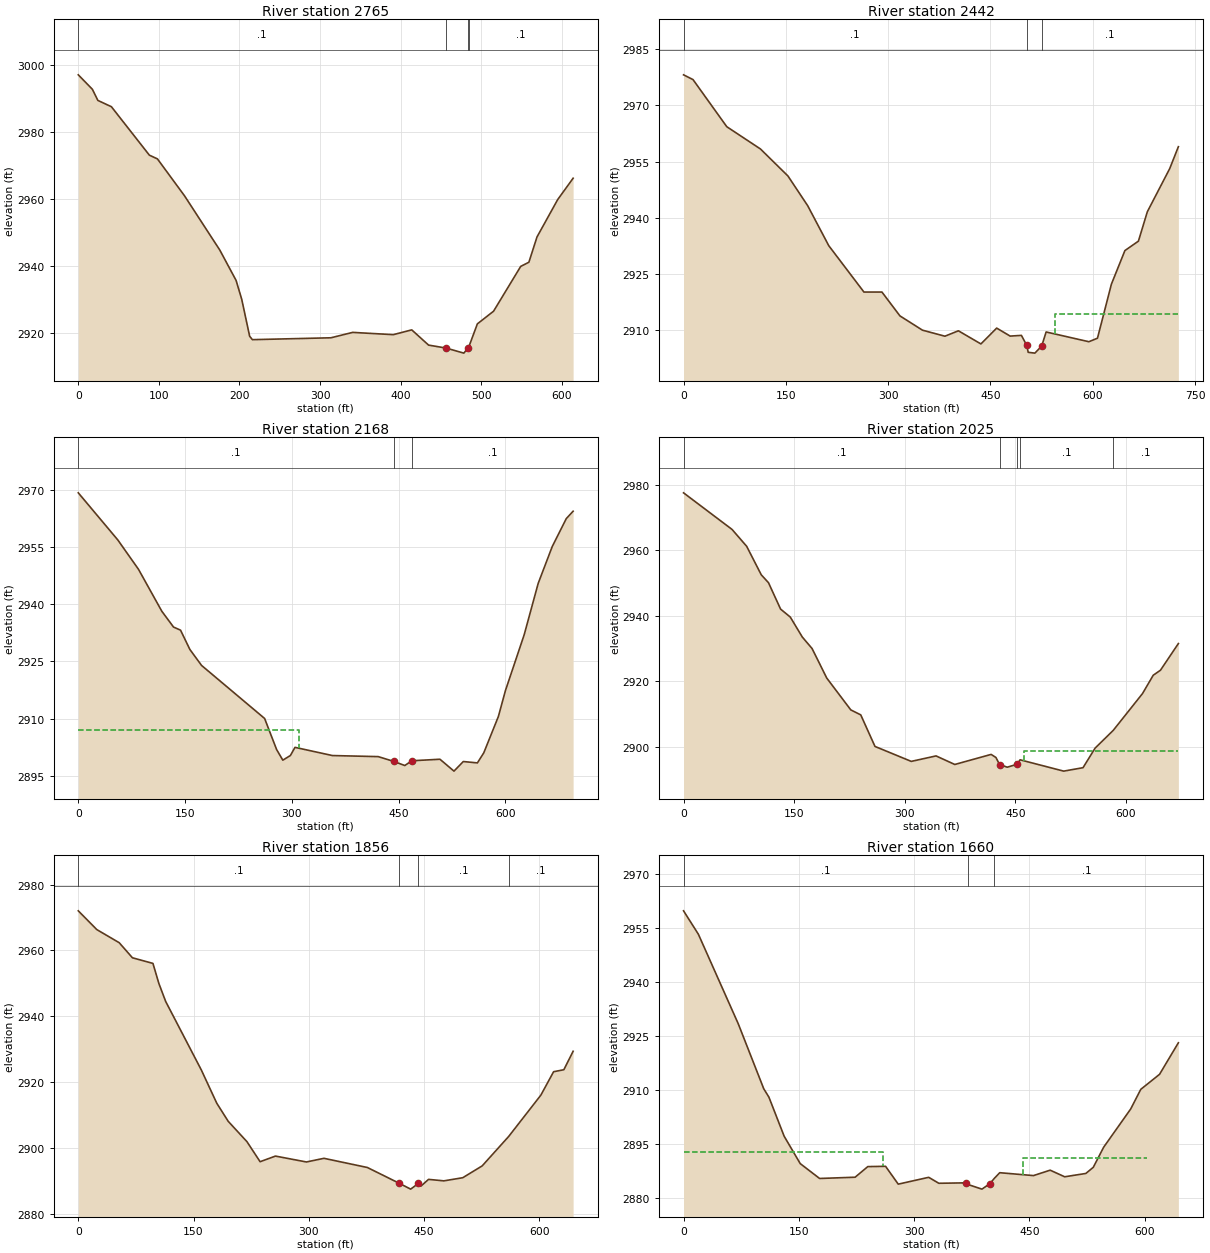
Type RM Length L Ch R = 1 ,2765    ,320.9,323.7,324.6
XS GIS Cut Line= 2
2093650.96410512365827.6944555372093052.07592467365962.655172258
#Sta/Elev= 30
       0 2997.06    17.5 2992.74    24.3 2989.42    41.1 2987.54    88.2 2973.08
    98.2 2971.97   131.9 2960.92   175.6 2944.75   195.8 2935.69   202.8 2930.05
   212.6 2919.04     216 2918.02   313.5 2918.58   340.4 2920.19   390.8 2919.51
   413.7 2920.94   434.6 2916.39  456.38 2915.51   478.3    2914  483.66 2915.59
     485 2916.14     485 2916.16     485 2916.19   495.1 2922.73   515.2 2926.51
   548.9 2939.89     559 2941.12   569.1 2948.68   594.8 2959.84   613.9  2966.2
#Mann= 4 ,-1 , 0
       0      .1       0  456.38    .045       0  483.66    .045       0
     485      .1       0
Bank Sta=456.38,483.66
XS Rating Curve= 0 ,0
Exp/Cntr=0.3,0.1

Type RM Length L Ch R = 1 ,2442    ,272.4,274,273.5
XS GIS Cut Line= 2
2093650.96410512365599.9482460692092929.16527194365673.453636427
#Sta/Elev= 30
       0 2978.13    13.9 2976.86    63.4  2964.3   112.8 2958.36   153.1 2951.16
   182.1 2943.22   212.9 2932.59   264.5 2920.22   290.9 2920.22   317.3 2913.86
   350.3 2910.06   383.2 2908.45     403 2909.89     436 2906.39   459.1 2910.61
   478.9 2908.48   495.4 2908.67   503.2    2906   505.3 2904.16   515.1 2903.94
   525.1 2905.83   531.6 2909.58   594.3 2906.98   606.9 2907.92   627.3 2922.32
   647.1 2931.28   666.9 2933.79     680 2941.63   712.8 2953.13   725.5 2958.97
#Mann= 3 ,-1 , 0
       0      .1       0   503.2    .045       0   525.1      .1       0
#XS Ineff= 2 , 0
       0                  544.63       0 2914.44
Permanent Ineff=
       F       F
Bank Sta=503.2,525.1
XS Rating Curve= 0 ,0
Exp/Cntr=0.3,0.1

Type RM Length L Ch R = 1 ,2168    ,141.5,142.2,142.5
XS GIS Cut Line= 3
     2093567.492      365367.801     2093112.414      365382.972
2092872.96615827365398.904942406
#Sta/Elev= 30
       0 2969.27    55.5 2956.91    84.6 2949.19   117.4 2938.17   133.8 2934.03
   143.7  2933.2   156.8 2928.14   173.2 2923.95   261.8 2910.02   278.7 2901.85
   287.4 2899.07     298 2900.28   304.5 2902.43   357.1 2900.28   421.4    2900
     443 2898.76   458.8 2897.66   468.7 2898.91   508.2 2899.31   527.9 2896.19
     541 2898.71   560.8 2898.35   569.8 2901.01   590.3 2910.54   600.2 2917.35
   626.5 2931.98   646.2 2945.48     666 2955.18   685.7  2962.5   695.3 2964.44
#Mann= 3 ,-1 , 0
       0      .1       0     443    .045       0   468.7      .1       0
#XS Ineff= 2 , 0
          309.56 2907.11
Permanent Ineff=
       F       F
Bank Sta=443,468.7
XS Rating Curve= 0 ,0
Exp/Cntr=0.3,0.1

Type RM Length L Ch R = 1 ,2025    ,169.7,169.3,166.6
XS GIS Cut Line= 2
2093548.94629021 365245.801249872092877.94029543365243.421795988
#Sta/Elev= 30
       0 2977.48    65.8 2966.31    85.6 2961.17   105.4 2952.47   115.2 2950.06
   131.6 2942.01   144.7 2939.59   161.1 2933.47   174.3 2929.98   194.2 2920.97
   226.8 2911.26   240.3 2909.74   259.6 2900.11   308.8 2895.55   342.4 2897.22
   367.8 2894.61   417.1 2897.68   423.6 2896.74   428.5  2894.6   438.9 2893.78
     452 2894.65   456.4 2896.03   515.5 2892.58   541.7 2893.63   558.1  2899.6
   582.7 2905.02   622.3 2916.22   636.9 2921.83   646.7 2923.36     671  2931.5
#Mann= 5 ,-1 , 0
       0      .1       0   428.5    .045       0     452    .045       0
   456.4      .1       0   582.7      .1       0
#XS Ineff= 2 , 0
                          461.27         2898.64
Permanent Ineff=
       F       F
Bank Sta=428.5,452
XS Rating Curve= 0 ,0
Exp/Cntr=0.3,0.1

Type RM Length L Ch R = 1 ,1856    ,194.7,195.9,196.6
XS GIS Cut Line= 2
2093487.08323482365040.8252767952092850.83985599365142.045814336
#Sta/Elev= 30
       0 2972.03    24.1 2966.34    53.3 2962.35    70.5 2957.78    97.2 2956.07
   104.9 2949.99   113.8 2944.51   160.3 2923.67   180.3 2913.63   195.2 2908.14
   219.6 2901.96   236.7 2895.88   256.7 2897.59     297  2895.8   319.8 2896.91
   376.3 2894.13   417.3  2889.4   432.7 2887.56   442.7 2889.28   446.1 2888.48
     456 2890.52   475.9 2890.07   500.5 2891.02   525.8 2894.61   560.6 2903.62
   560.6 2903.63   602.2 2916.09   618.8  2923.2   632.1 2923.79   644.2  2929.4
#Mann= 4 ,-1 , 0
       0      .1       0   417.3    .045       0   442.7      .1       0
   560.6      .1       0
Bank Sta=417.3,442.7
XS Rating Curve= 0 ,0
Exp/Cntr=0.3,0.1

Type RM Length L Ch R = 1 ,1660    ,275.6,277,275.4
XS GIS Cut Line= 3
2093396.38592146364879.835643051 2092945.8383497 364929.40782339
2092854.06725278365096.316764374
#Sta/Elev= 30
       0 2959.67    19.3 2953.19    71.2 2928.37   104.4 2910.35     111 2908.09
   130.9 2897.23   151.8 2889.65     177 2885.53   223.2 2885.88   239.7 2888.82
   262.8  2888.9   279.3 2883.96   318.9 2885.85   332.1  2884.2   367.2 2884.32
   370.12883.852   388.2 2882.58   398.5  2884.1   404.12885.516   411.3 2887.13
   455.2 2886.33   476.9 2887.83   495.8    2886   523.3 2886.92     533 2888.62
   546.5 2894.19   581.7 2904.79   594.8 2910.22   619.2 2914.38   643.7 2923.12
#Mann= 3 ,-1 , 0
       0      .1       0   370.1    .045       0   404.1      .1       0
#XS Ineff= 2 ,-1
       0  258.93 2892.98  441.16   603.1 2891.24
Permanent Ineff=
       F       F
Bank Sta=367.2,398.5
XS Rating Curve= 0 ,0
Exp/Cntr=0.3,0.1

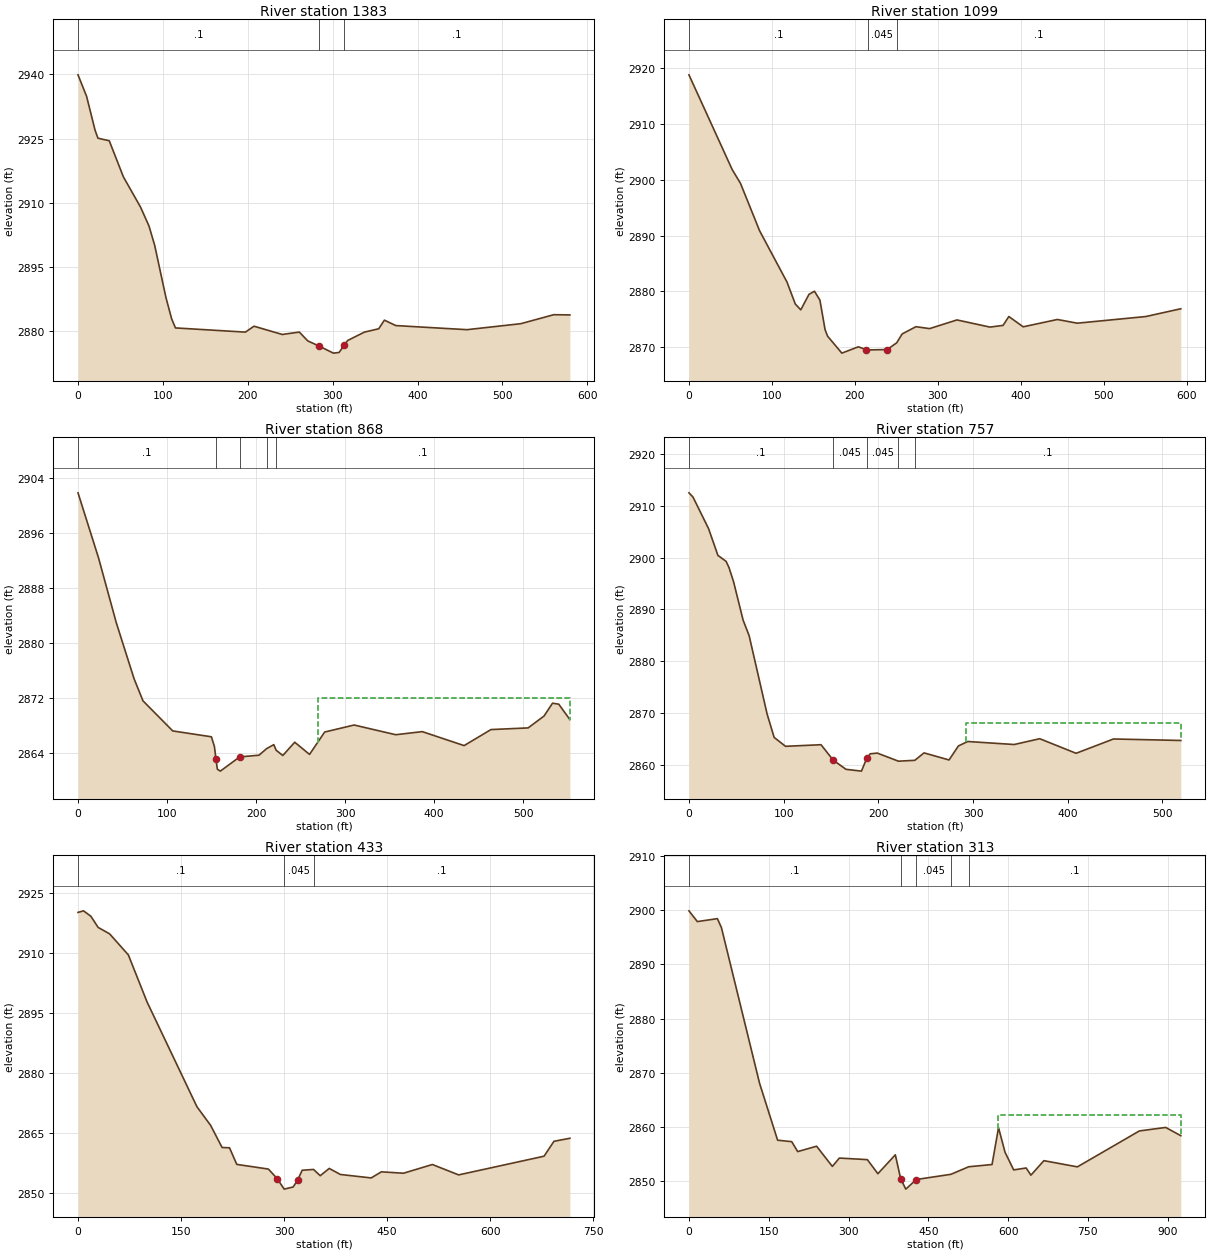
Type RM Length L Ch R = 1 ,1383    ,279.7,284.3,285.3
XS GIS Cut Line= 3
 2093348.5074989364628.7130882342092905.26834945 364714.07474519
2092858.57193688364833.319064887
#Sta/Elev= 30
       0  2939.9    10.1 2934.88    20.1 2926.95    23.5 2925.09    36.8 2924.49
    53.5 2916.04    73.6 2909.01    83.6 2904.58    90.3 2900.07   103.6 2887.84
   110.3 2882.88   114.8 2880.75   197.2 2879.77   207.3 2881.15   240.6 2879.22
   260.7 2879.78   270.7 2877.71   283.7 2876.54   300.8 2874.86   307.5 2875.01
   313.5 2876.67   317.5  2877.8   337.5 2879.78   354.2 2880.55   360.9 2882.57
   374.3  2881.3   458.2 2880.34   521.6 2881.74   560.4 2883.84   579.4 2883.79
#Mann= 3 ,-1 , 0
       0      .1       0   283.7    .045       0   313.5      .1       0
Bank Sta=283.7,313.5
XS Rating Curve= 0 ,0
Exp/Cntr=0.3,0.1

Type RM Length L Ch R = 1 ,1099    ,226.9,231.1,224.1
XS GIS Cut Line= 3
2093262.40632683364419.0054012232092886.54373396364464.413205247
2092822.27897451364668.864432616
#Sta/Elev= 30
       0 2918.76    52.1 2901.81    62.1 2899.35    85.2 2890.84   118.2 2881.67
   128.2 2877.74   134.8  2876.7   144.7 2879.47   151.3 2880.03   157.9 2878.43
   164.1 2873.15   167.1 2871.99   184.3 2868.95   204.2 2870.08   213.8 2869.56
   215.5 2869.52   238.9 2869.59   250.4 2870.79     257 2872.38   273.6 2873.68
   290.1 2873.34   323.1 2874.89   362.8 2873.61   378.6 2873.91   385.6  2875.5
   402.9 2873.66   444.1 2874.97   468.1 2874.31   550.7  2875.5   592.9 2876.89
#Mann= 3 ,-1 , 0
       0      .1       0   215.5    .045       0   250.4      .1       0
Bank Sta=213.8,238.9
XS Rating Curve= 0 ,0
Exp/Cntr=0.3,0.1

Type RM Length L Ch R = 1 ,868     ,107.4,110.6,110.7
XS GIS Cut Line= 4
2093239.75273436364222.5802380362092817.88681047364302.133204284
2092774.19604098364311.4955120312092743.11489923364383.444272878
#Sta/Elev= 30
       0 2901.86      23 2892.43      43 2882.98      63 2874.83      73 2871.63
   106.4 2867.26   149.8 2866.41   153.2    2865   154.9 2863.19   156.5  2861.7
   159.8 2861.42   181.6 2863.49   203.2 2863.73   211.92864.695   219.9 2865.27
   222.52864.458     230 2863.69   243.4 2865.62     260 2863.85     277  2867.1
   310.1 2868.12   356.8 2866.71   386.6 2867.16   433.6 2865.13   463.8 2867.46
   505.5  2867.7   523.4 2869.43   532.9 2871.29   539.9 2871.15   552.4 2868.91
#Mann= 5 ,-1 , 0
       0      .1       0   154.9    .045       0   181.6    .045       0
   211.9    .045       0   222.5      .1       0
#XS Ineff= 2 , 0
                             269            2872
Permanent Ineff=
       F       F
Bank Sta=154.9,181.6
XS Rating Curve= 0 ,0
Exp/Cntr=0.3,0.1

Type RM Length L Ch R = 1 ,757     ,320,324.3,323.7
XS GIS Cut Line= 3
2093218.08480553364130.1773014672092833.49065672364171.060895814
2092747.06844221364271.800887565
#Sta/Elev= 30
       0 2912.57     4.2 2911.78    20.7 2905.66    30.6 2900.47    39.3  2899.3
    42.3 2898.11    47.1  2895.4    57.2 2887.95    63.6 2884.92    82.5 2869.82
      90 2865.25     102 2863.53   139.5 2863.84   152.5 2860.83   165.9 2859.08
   182.2 2858.73   187.7 2861.18   191.4 2862.08   198.9 2862.22   221.32860.654
   238.62860.824   248.3 2862.26   274.7 2860.89   284.6  2863.6   294.5 2864.46
   343.5 2863.88   370.5    2865   408.9 2862.18   448.4 2864.95   519.5 2864.66
#Mann= 5 ,-1 , 0
       0      .1       0   152.5    .045       0   187.7    .045       0
   221.3    .045       0   238.6      .1       0
#XS Ineff= 2 , 0
                             293            2868
Permanent Ineff=
       F       F
Bank Sta=152.5,187.7
XS Rating Curve= 0 ,0
Exp/Cntr=0.3,0.1

Type RM Length L Ch R = 1 ,433     ,117.5,120.3,121.9
XS GIS Cut Line= 5
2093357.61400106363964.3832067432093172.04546374363845.110007811
2092986.29470223363852.2320668972092958.91855156363911.052829279
2092859.26639797364134.740863859
#Sta/Elev= 30
       0 2920.26       8 2920.66    18.7 2919.31    29.3 2916.51      46  2914.9
    73.3 2909.63   100.6 2897.83   173.2 2871.62   193.1 2866.97   209.8 2861.43
   220.6 2861.35   231.2  2857.2   277.2 2856.03     290 2853.65   300.2 2851.01
   313.3 2851.55   319.9  2853.3   326.4 2855.73   342.9 2855.94   352.7 2854.37
   365.8 2856.19     382 2854.68   426.9 2853.81   441.7 2855.34   473.9 2854.99
     516 2857.17   554.2 2854.57   678.6 2859.25     693 2862.98   716.2 2863.74
#Mann= 3 ,-1 , 0
       0      .1       0   300.2    .045       0   342.9      .1       0
#XS Ineff= 2 , 0
             264    2856     334            2854
Permanent Ineff=
       F       F
Bank Sta=290,319.9
XS Rating Curve= 0 ,0
Exp/Cntr=0.5,0.3

Type RM Length L Ch R = 1 ,313     ,31,28.5,23.6
XS GIS Cut Line= 6
 2093395.4682312363930.368265647 2093290.3750451363745.491846888
2093133.12837694363733.1777451852093019.49563189363732.512506994
2092819.99997696364006.0235079732092751.40749736364081.679989202
#Sta/Elev= 30
       0 2899.83    15.8 2897.85    53.5 2898.39    61.1 2896.73   132.8 2868.07
   166.7  2857.6   193.2 2857.33   204.5  2855.5     240 2856.49   269.6 2852.77
   282.8 2854.31   335.4 2854.02   355.2 2851.43     388 2854.91     398 2850.51
   407.7 2848.59   427.4 2850.36   492.6 2851.32     526 2852.71   569.8 2853.12
     582 2859.91   594.2 2855.39   610.5 2852.13     634 2852.48   642.9 2851.16
   667.3 2853.83   730.3 2852.69   846.7  2859.3   896.2 2859.95   924.7 2858.43
#Mann= 5 ,-1 , 0
       0      .1       0     398    .045       0   427.4    .045       0
   492.6    .045       0     526      .1       0
#XS Ineff= 2 , 0
                          581.67         2862.27
Permanent Ineff=
       F       F
Bank Sta=398,427.4
XS Rating Curve= 0 ,0
Exp/Cntr=0.5,0.3

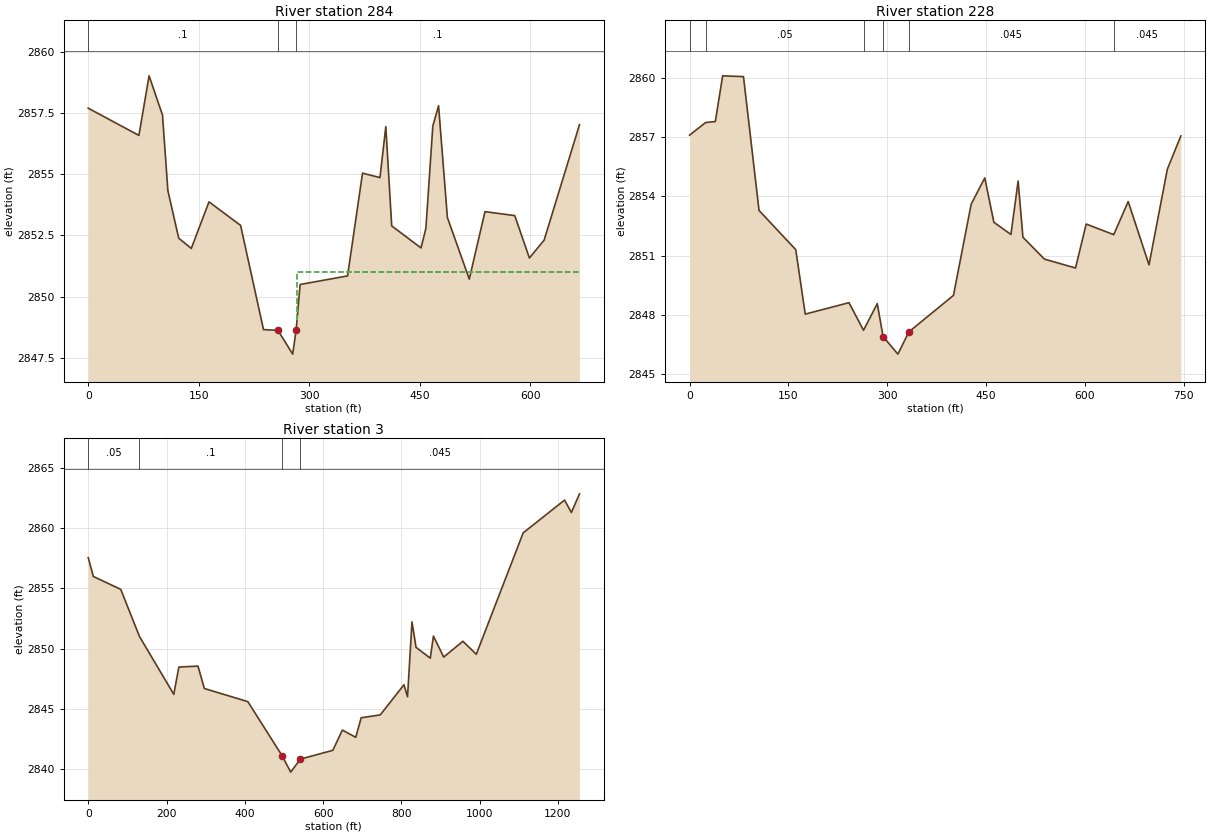
Type RM Length L Ch R = 1 ,284     ,55.2,55.9,55.5
XS GIS Cut Line= 5
2093337.37570526363726.9841578922093227.73011474363673.543449905
2093053.58711802363713.1632851372092964.21214087363737.119464579
2092809.41836601363962.860386245
#Sta/Elev= 30
       0 2857.69    68.8 2856.58    82.6 2859.01   100.8 2857.41   108.1 2854.33
   122.8 2852.39   139.9 2851.97   163.9 2853.87   206.8 2852.91   237.9 2848.66
   257.5 2848.63   277.5 2847.66  282.23 2848.65   287.6  2850.5     352 2850.85
   372.3 2855.04     396 2854.86   403.9 2856.94   411.9 2852.89   451.7 2851.99
   458.3 2852.79   467.7 2856.96   475.5 2857.79   487.5 2853.23   517.2 2850.72
   538.5 2853.47   578.9 2853.31   598.8 2851.58   618.8 2852.31   666.8 2857.02
#Mann= 3 , 0 , 0
       0      .1       0   257.5    .045       0  282.23      .1       0
#XS Ineff= 2 , 0
           219.2    2851  283.35            2851
Permanent Ineff=
       F       F
Bank Sta=257.5,282.23
XS Rating Curve= 0 ,0
Exp/Cntr=0.5,0.3

Type RM Length L Ch R = 1 ,228     ,225,225,225
XS GIS Cut Line= 6
 2093347.1565545363707.8333120852093177.01134492363620.838406718
2092969.32774404363687.2591765152092947.62709357363691.049888728
2092917.26993366363700.9707754852092796.19630223363955.987038636
#Sta/Elev= 30
       0 2857.11    24.3 2857.75    39.1  2857.8    50.2 2860.12    81.8 2860.08
   105.4 2853.29   161.1  2851.3   175.5 2848.03   241.9 2848.61   263.9 2847.21
   284.8 2848.56   293.6 2846.89   316.1    2846   332.8 2847.13   400.4 2848.98
   427.3 2853.61   447.9 2854.94   461.7 2852.69   487.6 2852.07   498.5 2854.78
   505.8 2851.93   538.4 2850.82   585.6 2850.37   601.8  2852.6   643.7 2852.06
   643.7 2852.07   665.5 2853.74   697.1 2850.53   724.9 2855.38   745.4 2857.07
#Mann= 6 ,-1 , 0
       0      .1       0    24.3     .05       0   263.9      .1       0
   293.6    .045       0   332.8    .045       0   643.7    .045       0
Bank Sta=293.6,332.8
XS Rating Curve= 0 ,0
Exp/Cntr=0.5,0.3

Type RM Length L Ch R = 1 ,3       ,3,3,3
XS GIS Cut Line= 6
2093400.43983404363689.625832755 2093158.0191291363474.644190611
2092978.47013885363513.0754704252092905.08178151363521.351215909
 2092854.5210261363534.1911037652092677.84882645364130.143161303
#Sta/Elev= 30
       0 2857.55    13.1 2855.99    83.1 2854.92   130.9 2851.01   218.6 2846.21
   231.6 2848.47   280.4 2848.55   296.7 2846.69   407.8  2845.6     495 2841.13
   517.3 2839.75     542 2840.83     625 2841.56   649.3 2843.24   683.5 2842.64
   697.4 2844.26   746.1  2844.5   806.7    2847   815.8 2846.01   827.2 2852.22
   837.5 2850.11   873.9 2849.21     882 2851.04   908.2  2849.3   957.3 2850.61
   991.5 2849.53  1111.3 2859.61    1217 2862.33  1234.4  2861.3  1255.2 2862.85
#Mann= 4 ,-1 , 0
       0     .05       0   130.9      .1       0     495    .045       0
     542    .045       0
Bank Sta=495,542
XS Rating Curve= 0 ,0
Exp/Cntr=0.3,0.1
LCMann Table=0

Chan Stop Cuts=-1
Use User Specified Reach Order=0
Composite Channel Slope=5